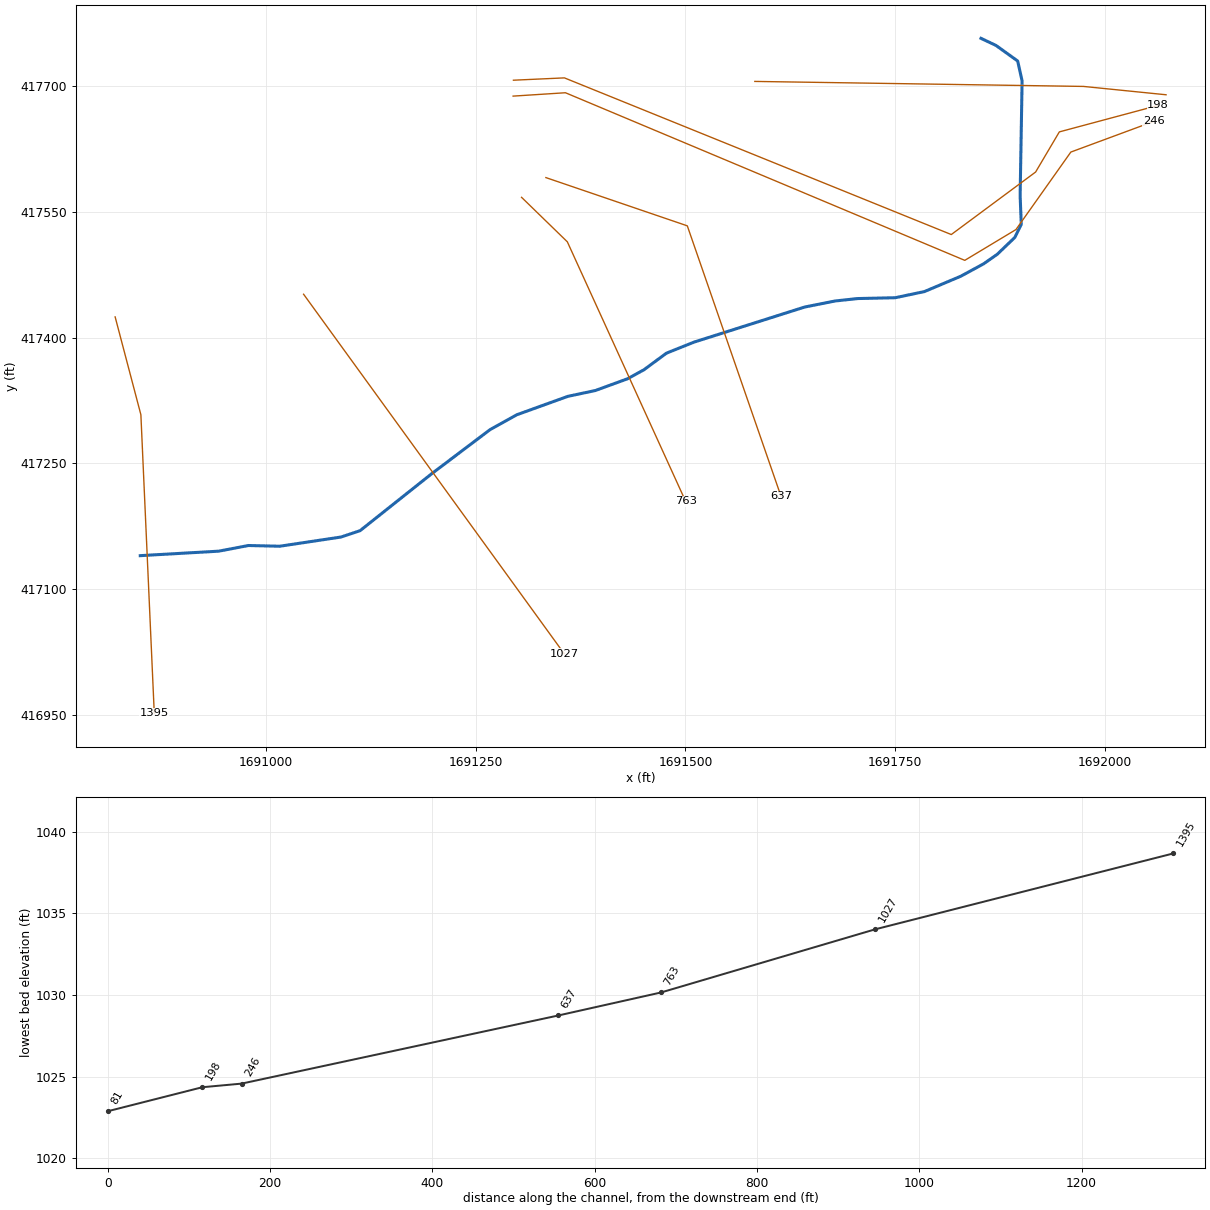
--- STYLESRN.prj (project) ---

Proj Title=STYLESRN
Current Plan=p01
Default Exp/Contr=0.3,0.1
English Units
Geom File=g01
Flow File=f01
Plan File=p01
Y Axis Title=Elevation
X Axis Title(PF)=Main Channel Distance
X Axis Title(XS)=Station
BEGIN DESCRIPTION:
---------- MODELED AS PART OF WVEMD CTP PROGRAM, 2023----------
Stream Name: Styles Run
Flood Zone:  AFH
Wetzel County, WV
HEC-RAS Version: RAS 6.3
Vertical Datum: NAVD88
Projection: NAD 1983 StatePlane West Virginia S FIPS 4702 (US Feet)
Terrain: 1-meter West Virginia FEMA R3 South Central (collected 2018-2020)
Land Use: 2019 NLCD
Hydrologic Method:
WV SIR2010-5033 regression equations
Additional Model Notes:
None
END DESCRIPTION:
DSS Export Rating Curves= 0
DSS Export Rating Curve Sorted= 0
DSS Export Volume Flow Curves= 0
DXF OffsetX= 0
DXF OffsetY= 0
DXF ScaleX= 1
DXF ScaleY= 10

--- STYLESRN.p01 (plan) ---

Plan Title=Floodplain
Program Version=6.30
Short Identifier=Floodplain
Geom File=g01
Flow File=f01
Subcritical Flow
K Sum by GR= 0
Std Step Tol= 0.01
Critical Tol= 0.01
Num of Std Step Trials= 20
Max Error Tol= 0.3
Flow Tol Ratio= 0.001
Split Flow NTrial= 30
Split Flow Tol= 0.02
Split Flow Ratio= 0.02
Log Output Level= 0
Friction Slope Method= 1
Unsteady Friction Slope Method= 2
Unsteady Bridges Friction Slope Method= 1
Parabolic Critical Depth
Global Vel Dist= 0 , 0 , 0
Global Log Level= 0
CheckData=True
Encroach Param=-1 ,0,0, 0
Computation Interval=1MIN
Output Interval=1HOUR
Instantaneous Interval=1HOUR
Mapping Interval=1HOUR
Computation Time Step Use Courant=        0
Computation Time Step Use Time Series=    0
Computation Time Step Count To Double=0
Computation Time Step Max Doubling=0
Computation Time Step Max Halving=0
Computation Time Step Residence Courant=0
Run HTab= 0
Run UNet= 0
Run Sediment= 0
Run PostProcess= 0
Run WQNet= 0
Run RASMapper=-1
UNET Theta= 1
UNET Theta Warmup= 1
UNET ZTol= 0.02
UNET ZSATol= 0.02
UNET MxIter= 20
UNET Max Iter WO Improvement= 0
UNET MaxInSteps= 0
UNET DtIC= 0
UNET DtMin= 0
UNET MaxCRTS= 20
UNET WFStab= 2
UNET SFStab= 1
UNET WFX= 1
UNET SFX= 1
UNET Gravity=32.17405
UNET 1D Methodology=Finite Difference
UNET DSS MLevel= 4
UNET Pardiso=0
UNET DZMax Abort= 100
UNET Use Existing IB Tables=-1
UNET Froude Reduction=False
UNET Froude Limit= 0.8
UNET Froude Power= 4
UNET D1 Cores= 0
UNET WindReference=Eulerian
UNET WindDragFormulation=Hsu (1988)
UNET D2 Coriolis=0
UNET D2 Cores= 0
UNET D2 Theta= 1
UNET D2 Theta Warmup= 1
UNET D2 Z Tol= 0.01
UNET D2 Volume Tol= 0.01
UNET D2 Max Iterations= 20
UNET D2 Equation= 0
UNET D2 RampUpFraction=0.1
UNET D2 TimeSlices= 1
UNET D2 Turbulence Formulation=None
UNET D2 Eddy Viscosity=0.3
UNET D2 Transverse Eddy Viscosity=0.1
UNET D2 Smagorinsky Mixing=0.05
UNET D2 BCVolumeCheck=0
UNET D2 Cores=0
UNET D2 SolverType=PARDISO (Direct)
UNET D2 Minimum Iterations= 3
UNET D2 Maximum Iterations= 30
UNET D2 Restart Number= 10
UNET D2 Relaxation Coeff=1.3
UNET D2 SOR Precondition Iterations= 10
UNET D2 ILUT Maximum Fill= 8
UNET D2 ILUT Tolerance=1E-08
UNET D2 Convergence Tolerance=0.00001
UNET D1D2 MaxIter= 0
UNET D1D2 ZTol=0.01
UNET D1D2 QTol=0.1
UNET D1D2 MinQTol=1
Write IC File= 0
Write IC File at Fixed DateTime=0
Write IC File at Sim End=0
Echo Input=False
Echo Parameters=False
Echo Output=False
Write Detailed= 0
HDF Write Warmup=0
HDF Write Time Slices=0
HDF Flush=0
HDF Compression= 1
HDF Chunk Size= 1
HDF Spatial Parts= 1
HDF Use Max Rows=0
HDF Fixed Rows= 1
Calibration Method= 0
Calibration Iterations= 20
Calibration Max Change=0.05
Calibration Tolerance=0.2
Calibration Maximum=1.5
Calibration Minimum=0.5
Calibration Optimization Method= 1
WQ AD Non Conservative
WQ ULTIMATE=-1
WQ Max Comp Step=1HOUR
WQ Output Interval=15MIN
WQ Output Selected Increments= 0
WQ Output face flow=0
WQ Output face velocity=0
WQ Output face area=0
WQ Output face dispersion=0
WQ Output cell volume=0
WQ Output cell surface area=0
WQ Output cell continuity=0
WQ Output cumulative cell continuity=0
WQ Output face conc=0
WQ Output face dconc_dx=0
WQ Output face courant=0
WQ Output face peclet=0
WQ Output face adv mass=0
WQ Output face disp mass=0
WQ Output cell mass=0
WQ Output cell source sink temp=0
WQ Output nsm pathways=0
WQ Output nsm derived pathways=0
WQ Create Restart=0
WQ Fixed Restart=0
WQ System Summary=0
WQ Write To DSS=0
Sorting and Armoring Iterations= 10
XS Update Threshold= 0.02
Bed Roughness Predictor= 0
Hydraulics Update Threshold= 0.02
Energy Slope Method= 1
Volume Change Method= 1
Sediment Retention Method= 0
Sediment TS Multiplier= 1
Warm Up Method= 0
XS Weighting Method= 0
Number of US Weighted Cross Sections= 1
Number of DS Weighted Cross Sections= 1
Upstream XS Weight=0
Main XS Weight=1
Downstream XS Weight=0
Number of DS XS's Weighted with US Boundary= 1
Upstream Boundary Weight= 1
Weight of XSs Associated with US Boundary= 0
Number of US XS's Weighted with DS Boundary= 1
Downstream Boundary Weight= 0.5
Weight of XSs Associated with DS Boundary= 0.5
Percentile Method= 0
Sediment Output Level= 3
Mass or Volume Output= 0
Output Increment Type= 1
Profile and TS Output Increment= 1
Transport Output Increment 1
XS Output Flag= 0
XS Output Increment= 10
Read HDF5 Sediment Hotstart= 0
Sediment Hotstart Type= 0
Write Gradation File= 0
Read Gradation Hotstart= 0
Write HDF5 File= 1
Write Binary Output= 1
Write DSS Sediment File= 0
DSS Sediment Output Type= 1
SV Curve= 0
Specific Gage Flag= 0
Subcell Erosion Methods= 0
Subcell Deposition Methods= 0
Advection Scheme= 1
Matrix Solver= 0
Implicit Weighting Factor= 1
Maximum Outer Loop Convergence Iterations= 5
Convergence Maximum Absolute= 0.001
Convergence RMSE= 0.0001
Grain Fractions Max Abs Error= 0.001
Max Subgrid Regions= 1
Max Subgrid Length Scale= 3.402823E+38
Initial Layer Thickness= 3.402823E+38
Min Layer Thickness= 3.402823E+38
Max Layer Thickness= 3.402823E+38
Number of Layers= 5

--- STYLESRN.f01 (steady flow) ---

Flow Title=Flow
Program Version=6.30
Number of Profiles= 1
Profile Names=F01pct
River Rch & RM=STYLESRN,Reach 1,1395
     568
Boundary for River Rch & Prof#=STYLESRN,Reach 1         , 1
Up Type= 0
Dn Type= 3
Dn Slope=0.01244
DSS Import GetInterval= 0
DSS Import GetPeak= 0
DSS Import FillOption= 0

--- STYLESRN.g01 (geometry) ---

Geom Title=Geometry
Program Version=6.30

River Reach=STYLESRN        ,Reach 1
Reach XY= 30
1690850.03926038417140.0239760071690943.58423735417145.361377096
1690978.97963404417152.1033574181691016.34144166417151.260609878
1691089.37956181417162.216327901 1691112.1337454417169.801055764
1691197.86652909417237.9792731191691267.29408079417290.399377057
1691298.93948611417307.9875520481691359.86951455417329.968342357
1691392.64442752417336.9089121631691431.13616572417350.977605792
1691450.67258443417361.7097831761691477.42819951 417381.45982912
1691510.48266321417394.6816145991691642.24695136417436.461614347
1691678.27052697417443.6445629581691705.46032713417446.580366543
1691750.27905665 417447.569397741691785.11691788417454.923356167
1691828.45019795417473.2172469211691855.66937758417488.021482316
1691871.87497491417499.3546275841691892.79665138417519.419443585
1691900.50839561 417534.985742121691899.16442677417569.419065733
1691901.51261051417706.1319330421691896.20451456417729.852486806
1691870.32754682417748.4308226221691852.44997335417756.863640296

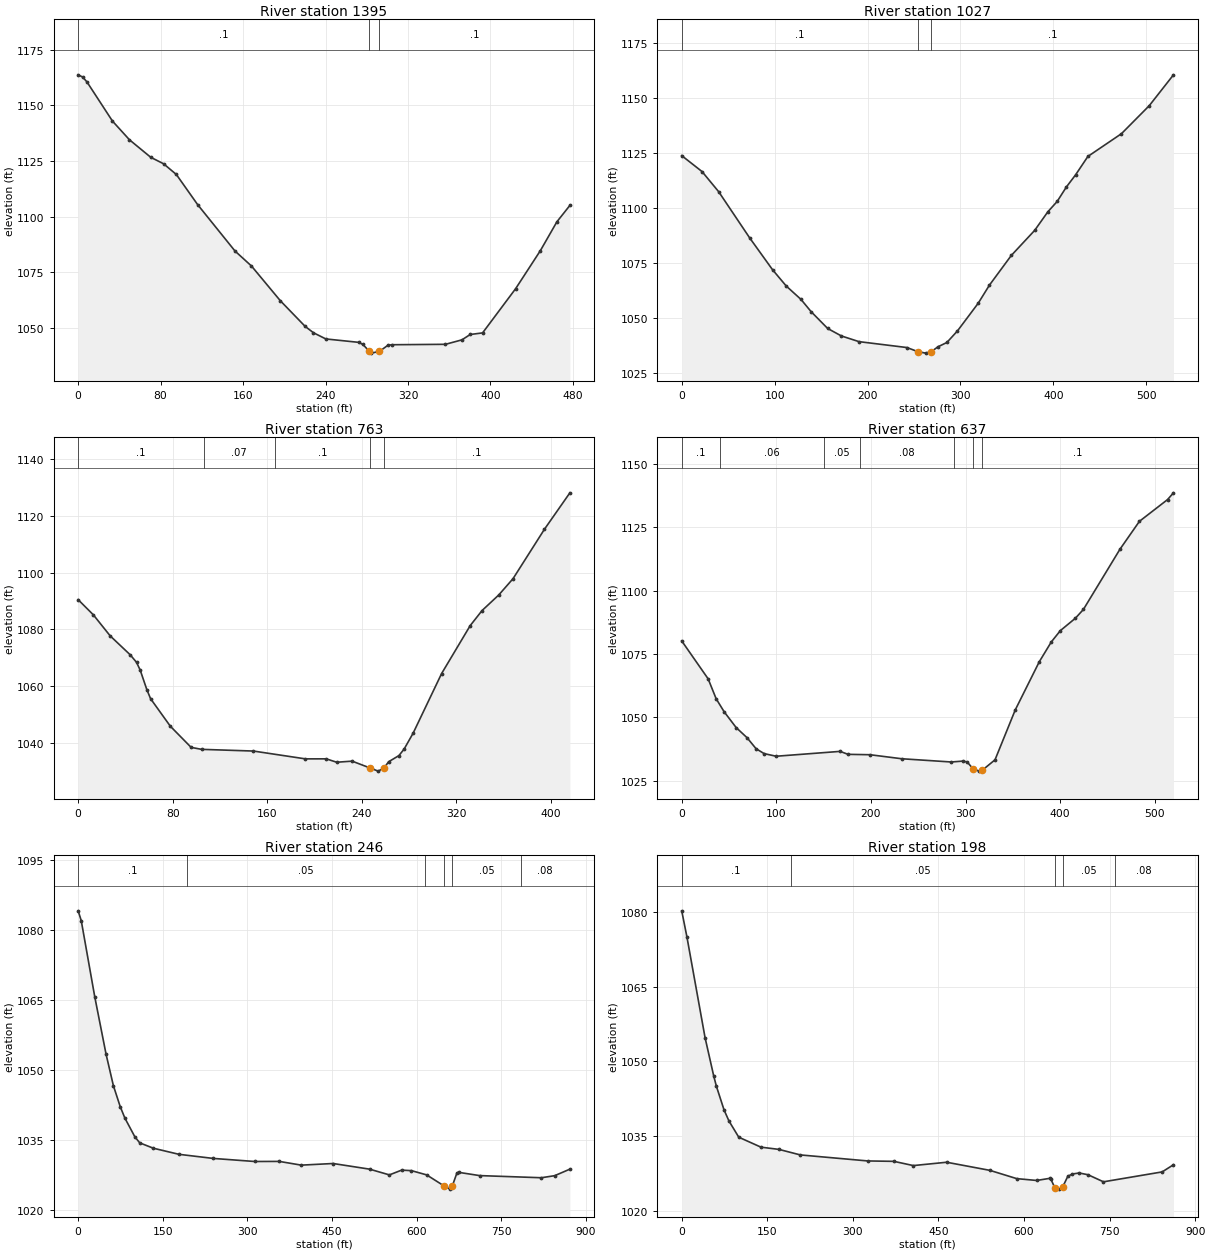
Type RM Length L Ch R = 1 ,1395    ,367.8,367.8,367.8
XS GIS Cut Line= 3
1690820.06360895417424.7176992581690850.76238888417308.062335553
1690866.72575444416951.956488456
#Sta/Elev= 30
       0 1163.67     4.3  1162.7     8.5 1160.53    33.3  1142.9    49.8 1134.49
    70.5 1126.61    82.9 1123.72    95.3  1118.9     116 1105.33   152.2 1084.52
   168.2 1077.78   196.2 1062.18   220.3 1050.65   228.3 1047.82   240.3 1045.03
   272.3  1043.5   276.3 1042.54   282.61039.438   284.3 1038.66   292.3 1039.41
   300.3 1042.12   304.3 1042.43   356.4 1042.62   372.4 1044.63   380.4 1047.03
   392.4 1047.75   424.5 1067.64   448.5 1084.73   464.5 1097.66   477.1 1105.02
#Mann= 3 ,-1,0
       0      .1       0   282.6    .045       0   292.3      .1       0
Bank Sta=282.6,292.3
XS Rating Curve= 0 ,0
Exp/Cntr(USF)=0,0
Exp/Cntr=0.3,0.1

Type RM Length L Ch R = 1 ,1027    ,263.5,263.5,263.5
XS GIS Cut Line= 2
1691044.77867799417451.732625589 1691355.4503308417023.177657875
#Sta/Elev= 30
       0 1123.89    21.9 1116.63    39.8 1107.46    73.1 1086.48    97.8 1071.94
   112.6 1064.51   128.4 1058.45   139.3 1052.87   157.1 1045.23   171.9 1041.82
   190.8 1039.24   242.4 1036.55   253.9 1034.73   262.5 1034.01   268.8 1034.72
   275.7 1036.87   285.4 1038.85   296.8 1044.12   319.2 1056.76   331.2 1064.95
   354.7 1078.44   379.9 1089.87   394.1 1098.34   404.1 1103.03     414  1109.6
   423.9 1115.13   437.2 1123.53   473.3 1133.87   503.2 1146.61   529.3 1160.66
#Mann= 3 ,-1,0
       0      .1       0   253.9    .045       0   268.8      .1       0
Bank Sta=253.9,268.8
XS Rating Curve= 0 ,0
Exp/Cntr(USF)=0,0
Exp/Cntr=0.3,0.1

Type RM Length L Ch R = 1 ,763     ,126.7,126.7,126.7
XS GIS Cut Line= 3
1691304.68067037417567.2950952611691359.25627912417514.235475642
1691500.24326839417204.973692722
#Sta/Elev= 30
       0 1090.46    12.9  1085.1    27.1 1077.72    44.1 1071.04    49.4 1068.41
    52.5 1065.69    58.1 1058.84    61.3 1055.62      78 1045.94    95.6  1038.5
   104.4 1037.81   148.3 1037.21   192.3 1034.46   209.9 1034.47   218.7 1033.28
   231.8 1033.66   247.1 1031.23   253.8 1030.15   258.8 1031.25   262.6 1033.43
   271.4 1035.62   275.8 1037.93   283.4 1043.51   307.5 1064.48   331.7 1081.34
   341.7 1086.62   355.8 1092.09   367.9 1097.83   394.5 1115.23     416 1128.02
#Mann= 5 ,-1,0
       0      .1       0  106.12     .07       0  166.12      .1       0
   247.1    .045       0   258.8      .1       0
Bank Sta=247.1,258.8
XS Rating Curve= 0 ,0
Exp/Cntr(USF)=0,0
Exp/Cntr=0.3,0.1

Type RM Length L Ch R = 1 ,637     ,390.2,390.2,390.2
XS GIS Cut Line= 3
1691333.69349759417590.812024087  1691502.311197417533.284224209
1691614.12630139417210.558926291
#Sta/Elev= 30
       0 1080.18    27.9 1065.21    36.4 1057.32    44.8 1052.21    57.5 1045.96
      69 1041.96    78.6 1037.59    87.1 1035.66    99.8 1034.62   167.4 1036.54
   175.8 1035.37     199 1035.22   232.5 1033.63   284.8 1032.35   297.5 1032.71
   301.7 1032.34   307.81029.699   314.4 1028.74   317.51029.051   331.1 1033.21
   352.5 1052.93   377.9 1071.96   390.6 1079.78   400.2 1084.26     416 1089.12
   424.5  1092.6   463.1 1116.37   483.7 1127.41   513.4 1135.99   519.7 1138.67
#Mann= 7 ,-1,0
       0      .1       0      40     .06       0     150     .05       0
  188.16     .08       0  288.16      .1       0   307.8    .045       0
   317.5      .1       0
Bank Sta=307.8,317.5
XS Rating Curve= 0 ,0
Exp/Cntr(USF)=0,0
Exp/Cntr=0.3,0.1

Type RM Length L Ch R = 1 ,246     ,48.3,48.3,48.3
XS GIS Cut Line= 6
1691294.58999918417687.9684749821691356.99400346417691.989212267
1691833.16299728417492.1307100361691894.19387604417528.846101353
1691959.63115114417621.2582074321692058.69673964 417657.90121265
#Sta/Elev= 30
       0  1084.2     5.5 1082.12    29.6  1065.7    49.6 1053.44    62.5 1046.74
    74.6 1042.25    82.8 1039.81   100.6 1035.77   109.3 1034.48   133.5 1033.33
   178.7 1032.03   239.4 1031.15   313.2 1030.49   356.6 1030.51   395.6 1029.71
     452 1030.06   516.7 1028.85   551.8 1027.62   573.5 1028.64   590.9 1028.53
   617.9 1027.62   648.9 1025.24   659.4 1024.57   663.3 1025.23   671.6 1028.05
   674.4 1028.17   711.7 1027.47   821.2 1027.01   844.8 1027.45   871.8 1028.85
#Mann= 6 ,-1,0
       0      .1       0  192.53     .05       0  615.61     .07       0
   648.9    .045       0   663.3     .05       0  784.42     .08       0
Bank Sta=648.9,663.3
XS Rating Curve= 0 ,0
Exp/Cntr(USF)=0,0
Exp/Cntr=0.3,0.1

Type RM Length L Ch R = 1 ,198     ,116.6,116.6,116.6
XS GIS Cut Line= 6
1691295.00081352417706.9397676261691355.77251272417709.710607644
1691817.06725262417522.9085931561691917.62833537417597.452431825
1691945.90695856417645.3085633741692063.65662219417676.860658349
#Sta/Elev= 30
       0 1080.25     9.1 1075.03    40.9 1054.79    56.2 1047.03    60.8 1045.01
    74.2 1040.26    82.8 1038.04     100 1034.78   138.9 1032.78   170.5 1032.33
   207.9 1031.22   326.2 1030.01   371.9 1029.93     406 1029.08   464.4 1029.75
   540.2 1028.12   587.2 1026.46   622.1 1026.09   644.8 1026.51     647 1026.37
   654.11024.604   661.9 1024.35   667.91024.812   676.8 1026.93   684.8 1027.39
   696.8 1027.59   712.2 1027.24   739.3 1025.82   842.2 1027.81     862 1029.25
#Mann= 5 ,-1,0
       0      .1       0  190.83     .05       0   654.1    .045       0
   667.9     .05       0  759.28     .08       0
Bank Sta=654.1,667.9
XS Rating Curve= 0 ,0
Exp/Cntr(USF)=0,0
Exp/Cntr=0.3,0.1

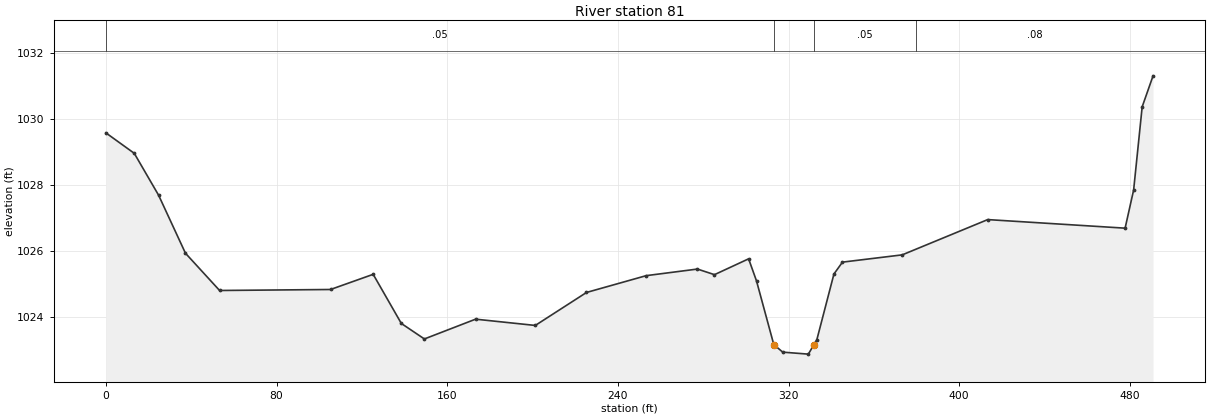
Type RM Length L Ch R = 1 ,81      ,,,
XS GIS Cut Line= 3
1691582.82017317417705.4897731291691974.70851815417699.521930312
1692073.17792462417689.575525618
#Sta/Elev= 30
       0 1029.59    13.3 1028.97    24.7  1027.7    37.3 1025.94    53.3 1024.81
   105.3 1024.84   125.3  1025.3   138.5 1023.81   149.3 1023.34   173.3 1023.94
   201.3 1023.75   225.3 1024.75   253.3 1025.26   277.3 1025.46   285.3 1025.29
   301.3 1025.77     305  1025.1   313.1 1023.17   317.3 1022.94   329.3 1022.88
   331.91023.166   333.3 1023.32   341.3 1025.31   345.3 1025.67   373.3 1025.89
   413.4 1026.96   477.8  1026.7   481.8 1027.86   485.8 1030.38   490.9 1031.32
#Mann= 4 ,-1,0
       0     .05       0   313.1    .045       0   331.9     .05       0
     380     .08       0
Bank Sta=313.1,331.9
XS Rating Curve= 0 ,0
Exp/Cntr(USF)=0,0
Exp/Cntr=0.3,0.1
LCMann Table=0

Chan Stop Cuts=-1
Use User Specified Reach Order=0
Composite Channel Slope=5